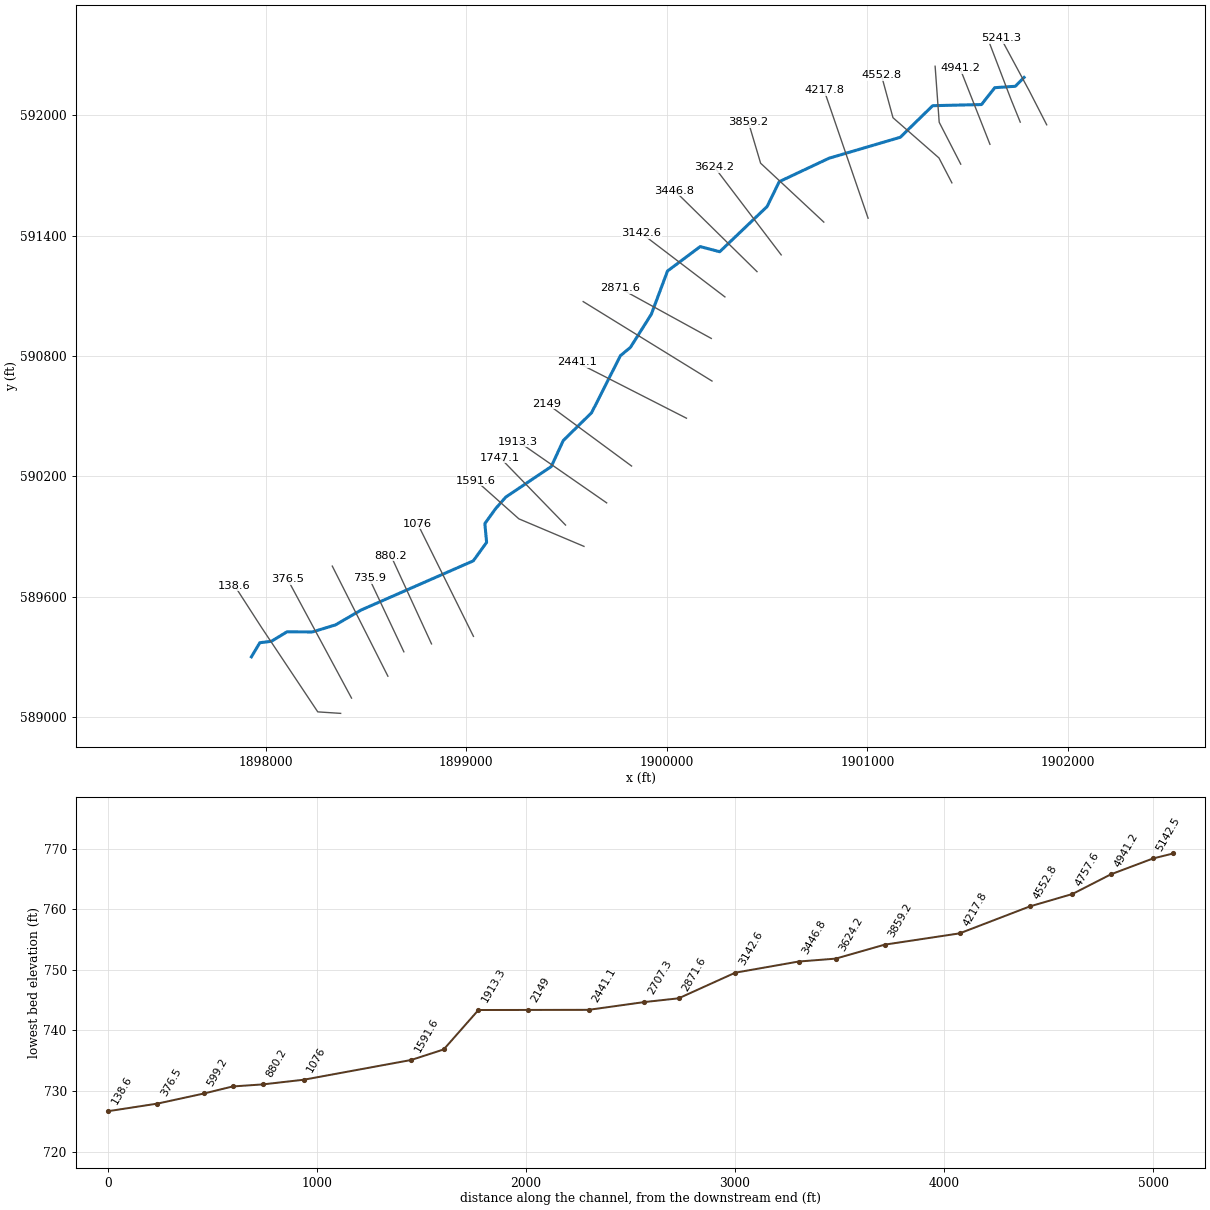
--- AshlyCmpRn.prj (project) ---

Proj Title=AshlyCmpRn
Current Plan=p01
Default Exp/Contr=0,0
English Units
Geom File=g01
Flow File=f01
Plan File=p01
BEGIN DESCRIPTION:
AMEC Environment & Infrastructure, 2013
Projection: NAD 1983 State Plane West Virginia South FIPS 4702 (US Feet)
Vertical Datum: NAVD 1988
END DESCRIPTION:
DSS Export Rating Curves= 0
DSS Export Rating Curve Sorted= 0
DSS Export Volume Flow Curves= 0
DXF OffsetX= 0
DXF OffsetY= 0
DXF ScaleX= 0
DXF ScaleY= 0

--- AshlyCmpRn.p01 (plan) ---

Plan Title=Floodplain
Program Version=4.00
Geom File=g01
Flow File=f01
K Sum by GR=0
Std Step Tol=0.01
Critical Tol=0.01
Num of Std Step Trials=20
Max Error Tol=0.3
Flow Tol Ratio=0.001
Split Flow NTrial=30
Split Flow Tol=0.02
Split Flow Ratio=0.02
Log Output Level=0
Friction Slope Method=1
Unsteady Friction Slope Method=2
Unsteady Bridges Friction Slope Method=1
Global Log Level=0
CheckData=False
Run HTab=0
Run UNet=0
Run PostProcess=0
UNET Theta=0
UNET Theta Warmup=0
UNET ZTol=0
UNET ZSATol=0
UNET MxIter=0
UNET MaxInSteps=0
UNET DtIC=0
UNET DtMin=0
UNET MaxCRTS=0
UNET WFStab=0
UNET SFStab=0
UNET WFX=0
UNET SFX=0
UNET DSS MLevel=0
UNET DZMax Abort=0
UNET Convert EG Bridges=0
UNET Use Existing IB Tables=0
UNET Froude Limit=0
UNET Froude Power=0
Write IC File=0
Echo Input=False
Echo Output=False
Write Detailed=0

--- AshlyCmpRn.f01 (steady flow) ---

Flow Title=NFF Regression Equation
Program Version=4.10
Number of Profiles= 1
Profile Names=P100yr
River Rch & RM=AshlyCmpRn,Main            ,5241.3
890.8133
River Rch & RM=AshlyCmpRn,Main            ,3446.8
971.2859
River Rch & RM=AshlyCmpRn,Main            ,376.5
1052.794
Boundary for River Rch & Prof#=AshlyCmpRn,Main            , 1
Up Type= 0
Dn Type= 3
Dn Slope=0.00611
DSS Import GetInterval= 0
DSS Import GetPeak= 0
DSS Import FillOption= 0

--- AshlyCmpRn.g01 (geometry) ---

Geom Title=USGS 3m DEM
Program Version=4.10

River Reach=AshlyCmpRn      ,Main
Reach XY= 30
     1901781.858      592189.493     1901738.269      592145.534
     1901635.522      592138.483     1901569.542      592054.372
     1901326.079      592048.723     1901164.598      591891.185
     1900808.543      591786.466      1900560.96      591669.826
     1900500.269      591545.674     1900264.052      591320.369
     1900166.845      591346.056     1900003.659       591224.17
     1899923.002      591008.819     1899818.964      590843.597
     1899768.773      590801.837     1899625.241        590517.7
     1899483.712       590378.69     1899424.093      590249.277
     1899196.911      590096.599     1899146.548      590039.286
     1899092.712      589964.606     1899101.601      589870.999
     1899035.117      589778.829     1898475.699      589533.574
     1898347.724      589459.277     1898232.134      589424.146
     1898105.967      589424.902     1898028.151      589377.684
     1897970.356      589370.506     1897928.586       589300.15

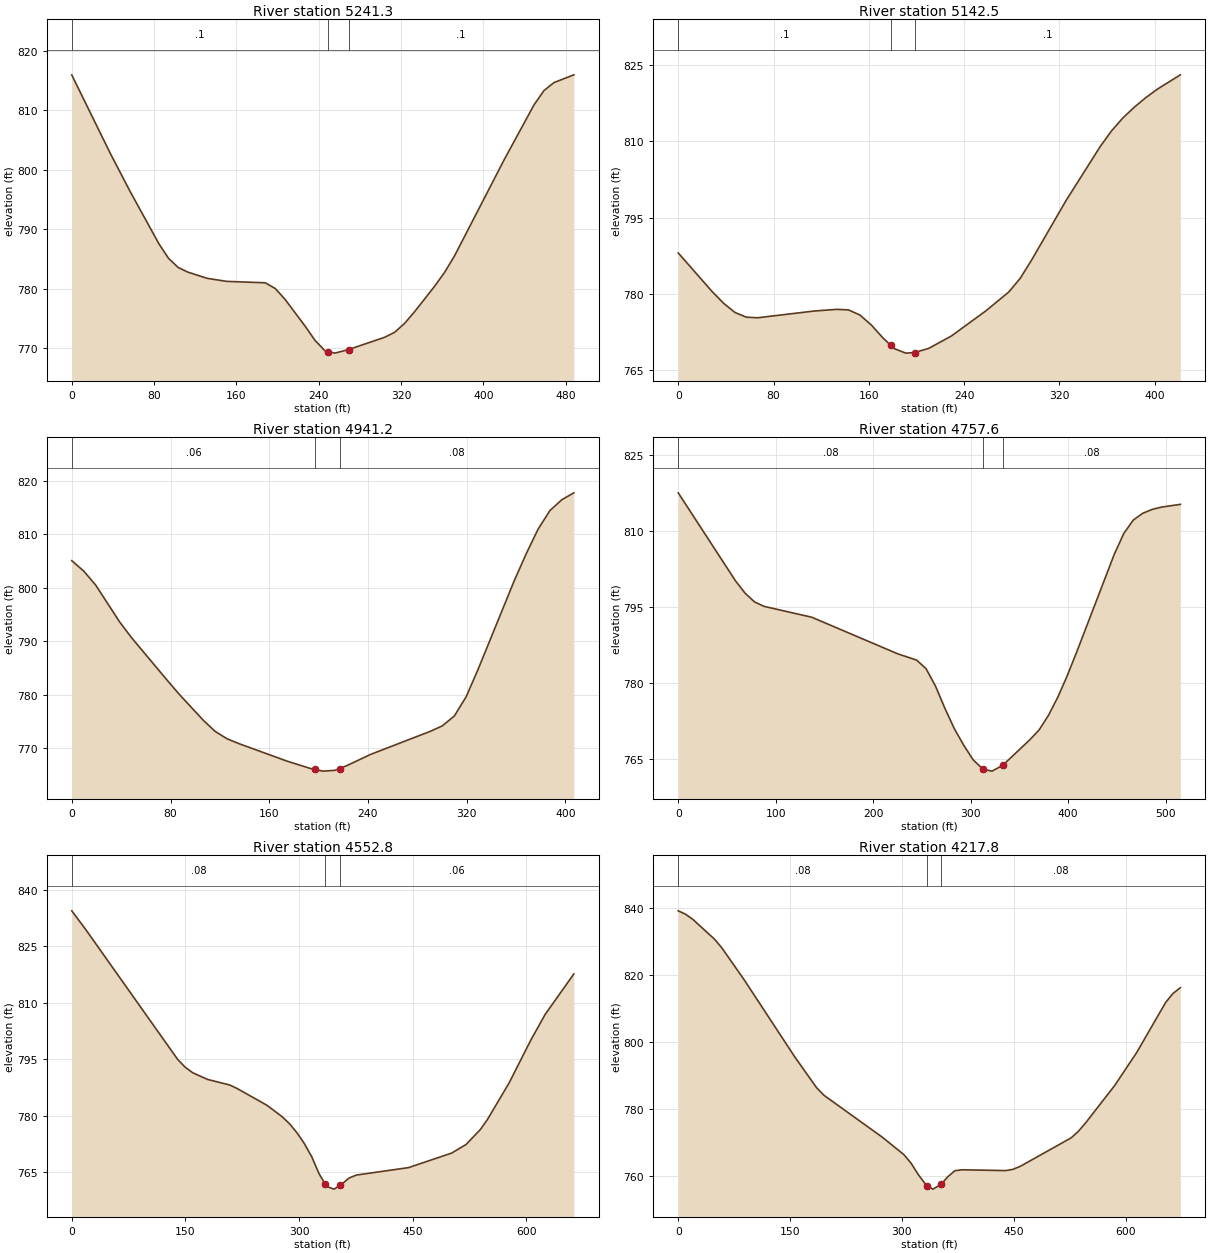
Type RM Length L Ch R = 1 ,5241.3  ,100.8,98.2,95.7
XS GIS Cut Line= 3
     1901894.712       591953.36       1901808.9      592120.607
     1901666.721      592384.606
#Sta/Elev= 30
       0  815.93    37.6   802.7    56.4  796.46    84.6   787.6      94  785.14
   103.4   783.6   112.8  782.82   131.6  781.78   150.4  781.27     188  781.03
   197.6  780.08   207.3  778.24   226.7  773.75   236.3  771.37     246  769.61
   248.9  769.49   255.7  769.22   268.9  769.82     304  771.88   313.7  772.72
   323.4  774.22   333.1  776.18   352.4  780.42   362.1  782.75   371.8  785.52
   420.1  801.69   449.1   810.9   458.8  813.31   468.5  814.65   487.8  815.95
#Mann= 3 , 0 , 0
       0      .1       0   248.9    .045       0   268.9      .1       0
Bank Sta=248.9,268.9
XS Rating Curve= 0 ,0
Exp/Cntr=0.3,0.1

Type RM Length L Ch R = 1 ,5142.5  ,201.3,201.3,201.3
XS GIS Cut Line= 3
     1901762.788      591966.711     1901716.227      592081.322
     1901609.974      592359.492
#Sta/Elev= 30
       0  788.08    28.6  780.45    38.1  778.18    47.6  776.38    57.1  775.45
    66.6  775.33   114.2  776.66   133.3  776.99   142.9  776.88   152.5  775.88
   162.1  773.91   171.7  771.41   178.4  769.92   181.3  769.28     191  768.38
   198.4   768.5   210.2   769.3   229.4  771.76   258.2  776.68   277.4  780.38
     287  783.05   296.6  786.66   325.4  798.31   354.2  808.98   363.8  812.09
   373.4  814.65   383.1  816.78   392.7  818.64   402.3  820.29   421.5   823.1
#Mann= 3 , 0 , 0
       0      .1       0   178.4    .045       0   198.4      .1       0
Bank Sta=178.4,198.4
XS Rating Curve= 0 ,0
Exp/Cntr=0.3,0.1

Type RM Length L Ch R = 1 ,4941.2  ,191.6,183.6,175.4
XS GIS Cut Line= 2
     1901611.673      591856.218      1901462.44      592234.673
#Sta/Elev= 30
       0  805.06     9.7  803.12    19.4   800.5    38.7  793.65    48.4  790.69
    77.5  782.68    87.2  780.08   106.6  775.25   116.2  773.17   125.9  771.79
   135.6  770.88   174.4  767.63   193.7  766.23     197  766.07   203.4  765.76
   213.1   765.9     217  766.25   222.8  766.78   242.2  768.89   290.6   773.2
   300.3  774.22     310  776.06   319.6  779.67   329.3  784.81   358.4  801.25
   368.1   806.3   377.8  810.93   387.4  814.41   397.1  816.45   406.8  817.73
#Mann= 3 , 0 , 0
       0     .06       0     197    .045       0     217     .08       0
Bank Sta=197,217
XS Rating Curve= 0 ,0
Exp/Cntr=0.3,0.1

Type RM Length L Ch R = 1 ,4757.6  ,185,204.7,224.4
XS GIS Cut Line= 3
     1901466.021      591757.127     1901358.573      591966.054
     1901338.278      592245.418
#Sta/Elev= 30
       0   817.5    58.7  800.12    68.5  797.69    78.3  795.94    88.1  795.07
     137  792.92   225.2  785.69   244.6  784.45   254.2  782.76   263.9  779.31
   273.6   774.9   283.2  770.91   292.9  767.62   302.6  764.73   312.8  762.86
   321.9  762.52   332.8  763.66   360.5  768.69   370.2  770.67   379.8  773.55
   389.5  777.19   399.1   781.4   408.8  786.09   447.4  805.42   457.1  809.49
   466.7  812.11   476.4  813.45   486.1  814.22   495.7  814.68     515  815.22
#Mann= 3 , 0 , 0
       0     .08       0   312.8    .045       0   332.8     .08       0
Bank Sta=312.8,332.8
XS Rating Curve= 0 ,0
Exp/Cntr=0.3,0.1

Type RM Length L Ch R = 1 ,4552.8  ,348,334.9,321.9
XS GIS Cut Line= 4
     1901421.848      591664.006     1901357.379      591788.168
     1901128.158      591988.737       1901070.8      592199.339
#Sta/Elev= 30
       0  834.34    18.6  829.33   139.9  794.87   149.7  792.83   159.6  791.36
   179.2  789.59   208.7  788.09   218.5  787.15   257.8   782.7   277.4  779.73
   287.3  777.86   297.1  775.47   306.9   772.6   316.8  769.04   326.6   764.5
   334.7  761.76   336.4  761.18   346.2  760.46   354.7  761.48   365.9  763.39
   375.7  764.19   444.5  766.17   501.4  770.02   520.4  772.29   539.4  776.28
   548.9     779   577.4  788.67   605.8  799.94   624.8   806.8   662.8  817.59
#Mann= 3 , 0 , 0
       0     .08       0   334.7    .045       0   354.7     .06       0
Bank Sta=334.7,354.7
XS Rating Curve= 0 ,0
Exp/Cntr=0.3,0.1

Type RM Length L Ch R = 1 ,4217.8  ,345.9,358.2,370.6
XS GIS Cut Line= 2
     1901003.869      591487.758     1900785.157       592124.48
#Sta/Elev= 30
       0  839.03     9.8  838.02    19.5   836.5    48.8  830.54    58.5  827.97
    87.8  818.66   156.1  795.52   185.4  786.31   195.1  784.06   273.2  771.58
   302.5  766.33   312.2  763.76     322  760.32   332.9   757.1   341.5  756.02
   352.9   757.5     361  759.62   370.8   761.5   380.5  761.79   439.1  761.55
   448.8  761.92   458.6  762.82   526.9  771.32   536.6  773.27   546.4  775.82
   585.4  786.99   614.7  796.76   653.7  811.76   663.5  814.39   673.2  816.11
#Mann= 3 , 0 , 0
       0     .08       0   332.9    .045       0   352.9     .08       0
Bank Sta=332.9,352.9
XS Rating Curve= 0 ,0
Exp/Cntr=0.3,0.1

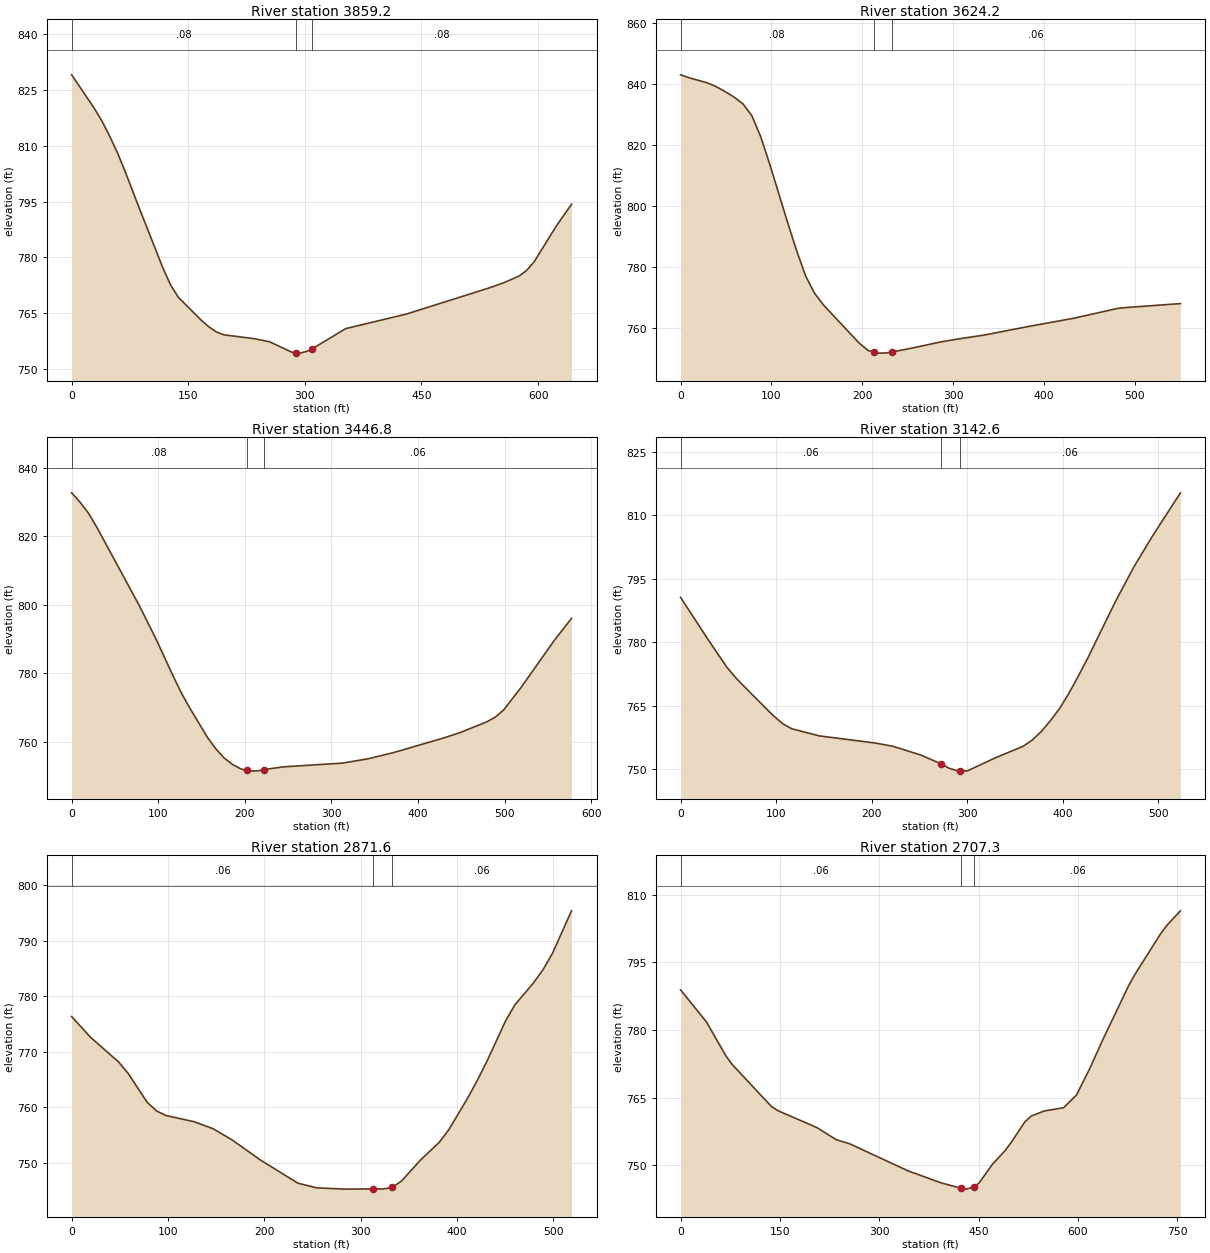
Type RM Length L Ch R = 1 ,3859.2  ,239.1,234.8,230.5
XS GIS Cut Line= 3
     1900783.131      591468.212     1900467.951      591761.903
     1900407.468      591965.303
#Sta/Elev= 30
       0  829.12    29.4  820.01    39.2  816.57      49  812.56    58.8  808.18
    68.5  803.25    88.1   792.6   117.5  777.04   127.3  772.52   137.1  769.24
   166.4  763.09   176.2  761.29     186  759.89   195.8  759.09     235  758.05
   254.6  757.22   283.9  754.35   289.1  754.25   293.7  754.16   303.5  754.69
   309.1  755.28   352.5  760.76   430.8  764.69   536.9  771.71   556.2  773.14
   575.5  774.91   585.1   776.4   594.8  778.72   623.7  788.48     643  794.26
#Mann= 3 , 0 , 0
       0     .08       0   289.1    .045       0   309.1     .08       0
Bank Sta=289.1,309.1
XS Rating Curve= 0 ,0
Exp/Cntr=0.3,0.1

Type RM Length L Ch R = 1 ,3624.2  ,173.6,177.2,180.9
XS GIS Cut Line= 2
     1900570.623      591304.653     1900237.535      591742.801
#Sta/Elev= 30
       0  842.98     9.8  841.99    29.5  840.35    39.3   839.1    49.1   837.5
      59  835.67    68.8  833.44    78.6  829.52    88.4   822.6    98.3  813.62
   117.9   794.6   127.8  785.41   137.6  777.19   147.4  771.52   157.2  767.67
   196.6  755.15   206.4  752.74   212.6  752.18   216.2  751.85     226   751.9
   232.6  752.21   255.5  753.54     285  755.43   304.7  756.44   334.2  757.76
   383.3  760.59   432.4  763.24   481.6  766.51   491.4   766.8   550.4  768.07
#Mann= 3 , 0 , 0
       0     .08       0   212.6    .045       0   232.6     .06       0
Bank Sta=212.6,232.6
XS Rating Curve= 0 ,0
Exp/Cntr=0.3,0.1

Type RM Length L Ch R = 1 ,3446.8  ,299.4,303,306.6
XS GIS Cut Line= 2
     1900450.043      591221.082     1900038.166      591625.715
#Sta/Elev= 30
       0   832.7     9.8  829.94    19.6  826.69    29.4  822.49    78.3  799.68
    97.9  789.73   117.4  779.05   127.2  773.99     137  769.57   156.6  761.34
   166.4  757.92   176.2   755.2   185.9   753.3   195.7  751.99   202.1  751.59
   205.5  751.37   215.3  751.47   222.1  751.82   244.6  752.62   313.2  753.72
   342.5  754.98   371.9  756.79   430.6  761.12   450.2  762.78   479.5  765.77
   489.3  767.13   499.1  769.28   518.7  775.67   557.8  789.67   577.4  796.01
#Mann= 3 , 0 , 0
       0     .08       0   202.1    .045       0   222.1     .06       0
Bank Sta=202.1,222.1
XS Rating Curve= 0 ,0
Exp/Cntr=0.3,0.1

Type RM Length L Ch R = 1 ,3142.6  ,266.1,270.7,275.3
XS GIS Cut Line= 2
     1900289.925      591095.103     1899873.929      591412.052
#Sta/Elev= 30
       0  790.63      29  780.58    48.4  774.12    58.1  771.52    67.8  769.28
    96.8   762.7   106.5  760.81   116.2  759.56   145.3  757.86   203.4  756.19
   222.8  755.37   251.8   753.3   272.4  751.26   280.9  750.23   290.5  749.53
   292.4  749.54   300.2   749.6   329.3  752.67   358.3  755.39     368  756.88
   377.7  758.96   387.4  761.57   397.1  764.52   406.8  768.14   416.4   772.1
   426.1  776.29   455.2  789.73   474.6  797.96   493.9  805.17     523  815.36
#Mann= 3 , 0 , 0
       0     .06       0   272.4    .045       0   292.4     .06       0
Bank Sta=272.4,292.4
XS Rating Curve= 0 ,0
Exp/Cntr=0.3,0.1

Type RM Length L Ch R = 1 ,2871.6  ,165,164.3,163.7
XS GIS Cut Line= 2
     1900222.015      590887.994     1899767.152      591137.512
#Sta/Elev= 30
       0  776.37    19.6  772.64    48.9  768.17    58.7  766.12    78.3  760.95
    88.1  759.38    97.9  758.55   127.2  757.44   146.8  756.17   166.4  754.18
   195.8  750.56   234.9  746.36   254.5  745.53   283.9   745.3   313.2  745.34
  323.05  745.32   332.8  745.61   342.6   746.8   362.2  750.56   381.8  753.78
   391.6  756.04   411.1  761.72   420.9  764.84   430.7   768.2   450.3  775.57
   460.1   778.5   479.6  782.49   489.4  784.86   499.2  787.81   518.8  795.41
#Mann= 3 , 0 , 0
       0     .06       0   313.2    .045       0   332.8     .06       0
Bank Sta=313.2,332.8
XS Rating Curve= 0 ,0
Exp/Cntr=0.3,0.1

Type RM Length L Ch R = 1 ,2707.3  ,264.6,265.8,267
XS GIS Cut Line= 2
     1900225.544      590675.571     1899583.157      591071.757
#Sta/Elev= 30
       0  788.88    39.2  781.74    68.6   774.2    78.4  772.25   137.2  763.01
     147  762.08   205.8  758.34   235.2  755.63   254.8  754.77   343.1  748.76
   392.1  746.13   423.7  744.86   431.3  744.68   443.7  745.24   450.9  746.08
   470.5  750.12   490.1  753.25   499.9  755.17   519.5  759.54   529.3  760.87
   548.9  762.01   578.3  762.74   597.9  765.58   617.5  771.32   637.1   777.7
   676.3  789.75   686.1  792.33   725.3  801.45   735.1  803.33   754.7  806.41
#Mann= 3 , 0 , 0
       0     .06       0   423.7    .045       0   443.7     .06       0
Bank Sta=423.7,443.7
XS Rating Curve= 0 ,0
Exp/Cntr=0.3,0.1

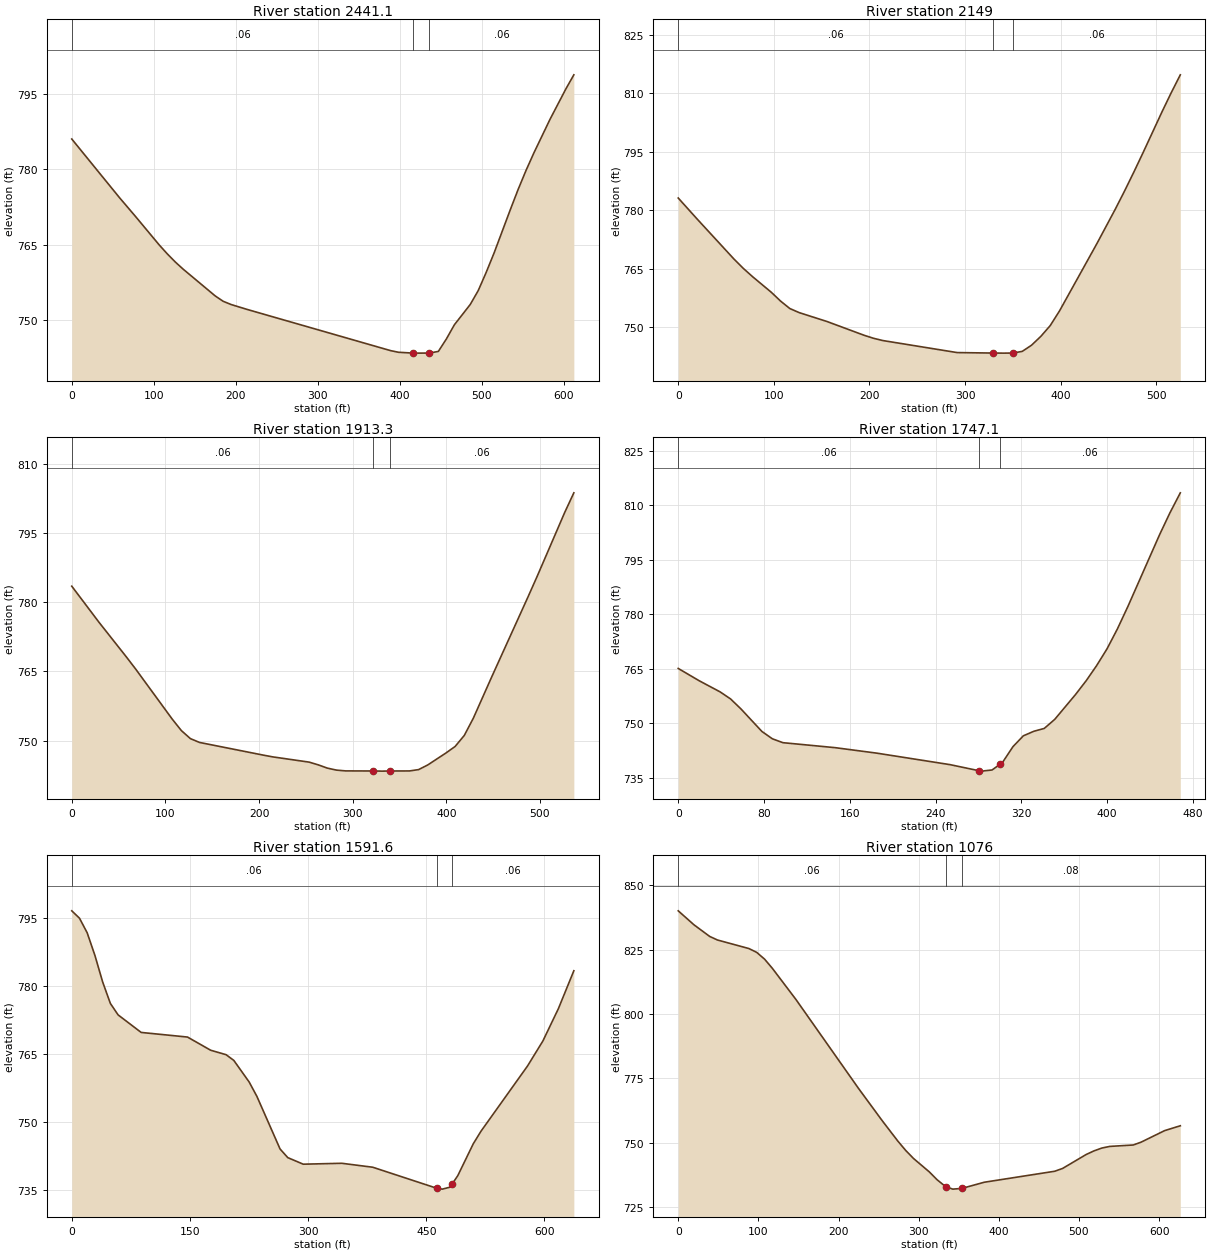
Type RM Length L Ch R = 1 ,2441.1  ,296.3,292.1,287.8
XS GIS Cut Line= 2
     1900098.124      590490.218     1899552.661      590768.255
#Sta/Elev= 30
       0  786.07    58.3  774.36    77.7  770.64   106.9  764.91   116.6  763.16
   126.3  761.55     136  760.11   174.9   754.8   184.6  753.73   194.4  753.08
   213.8  752.11   388.7   743.9   398.4  743.57   415.9  743.41   417.9   743.4
   435.9  743.41     447  743.74   456.8  746.23   466.5  749.04   485.9   753.1
   495.6  755.86   505.3  759.48   515.1  763.42   534.5  771.88   544.2  775.99
   553.9  779.81   563.6  783.34   583.1  789.98   602.5  796.06   612.2  798.86
#Mann= 3 , 0 , 0
       0     .06       0   415.9    .045       0   435.9     .06       0
Bank Sta=415.9,435.9
XS Rating Curve= 0 ,0
Exp/Cntr=0.3,0.1

Type RM Length L Ch R = 1 ,2149    ,234.7,235.5,236.3
XS GIS Cut Line= 2
     1899824.458      590251.665      1899401.83      590563.263
#Sta/Elev= 30
       0  783.17    19.4  777.88    58.3  767.51    68.1  765.11    77.8  762.98
    97.2  759.02     107  756.74   116.7  754.82   126.4  753.78   155.6  751.49
   194.5  747.95   204.2  747.19   213.9  746.61   291.7  743.52     329   743.4
  340.38  743.38     350   743.4   359.8  743.83   369.5  745.41   379.2  747.67
     389  750.43   398.7  754.18   437.6  771.36     457  780.26   466.7  784.92
   476.5  789.82   486.2  794.83   505.6  805.09   515.4  810.08   525.1  814.77
#Mann= 3 , 0 , 0
       0     .06       0     329    .045       0     350     .06       0
Bank Sta=329,350
XS Rating Curve= 0 ,0
Exp/Cntr=0.3,0.1

Type RM Length L Ch R = 1 ,1913.3  ,171,166.1,161.2
XS GIS Cut Line= 2
     1899700.203      590068.021     1899259.667       590373.65
#Sta/Elev= 30
       0  783.43    29.2  775.58    58.5  768.06    68.2  765.49   107.2  754.66
     117  752.16   126.7  750.41   136.5  749.58   204.7  746.83   214.5  746.46
   253.5  745.32   263.2  744.73     273  744.02   282.7  743.59   292.5  743.42
   321.7   743.4  331.45  743.37   340.3   743.4   360.7  743.41   370.4   743.7
   380.2  744.71   399.7  747.31   409.4  748.71   419.2   751.1   428.9  754.85
   448.4  763.74   487.4  781.17   497.2  785.64   526.4  799.38   536.2  803.65
#Mann= 3 , 0 , 0
       0     .06       0   321.7    .045       0   340.3     .06       0
Bank Sta=321.7,340.3
XS Rating Curve= 0 ,0
Exp/Cntr=0.3,0.1

Type RM Length L Ch R = 1 ,1747.1  ,153.7,155.5,157.3
XS GIS Cut Line= 2
     1899495.138       589957.34     1899168.765      590293.114
#Sta/Elev= 30
       0  765.12    19.5  761.74      39  758.68    48.8  756.73    58.5  753.98
      78  747.79    87.8  745.76    97.6  744.69   146.3  743.32   185.4   741.8
   253.6  738.64   280.2  736.99   282.9  736.86   292.7  737.17   300.2  738.76
   302.4  739.22   312.2  743.59   321.9  746.58   331.7  747.83   341.4  748.61
   351.2  751.11   370.7  757.99   380.5  761.74   390.2  765.88     400  770.54
   409.7  776.04   419.5  782.23   448.8  801.82   458.5  807.87   468.3  813.45
#Mann= 3 , 0 , 0
       0     .06       0   280.2    .045       0   300.2     .06       0
Bank Sta=280.2,300.2
XS Rating Curve= 0 ,0
Exp/Cntr=0.3,0.1

Type RM Length L Ch R = 1 ,1591.6  ,524.5,514,503.5
XS GIS Cut Line= 3
     1899587.084      589851.036     1899262.353       589988.33
      1899049.64      590177.645
#Sta/Elev= 30
       0  796.61     9.8  794.98    19.6  791.74    29.4  786.75    39.2   780.9
      49  776.15    58.8  773.62    88.1  769.74   146.9  768.72   176.3  765.81
   195.9  764.82   205.7  763.56   225.2  758.78     235  755.61   264.4  743.99
   274.2  742.08   293.8  740.63   342.8  740.83     382  739.96   463.2  735.32
   470.4  735.12   480.2  735.56   483.2  736.34     490   738.1   509.7  745.16
   519.5  747.93   578.4   762.3     598  767.85   617.7     775   637.3  783.37
#Mann= 3 , 0 , 0
       0     .06       0   463.2    .045       0   483.2     .06       0
Bank Sta=463.2,483.2
XS Rating Curve= 0 ,0
Exp/Cntr=0.3,0.1

Type RM Length L Ch R = 1 ,1076    ,196.5,195.8,195.1
XS GIS Cut Line= 2
     1899035.881      589402.248     1898757.591      589963.496
#Sta/Elev= 30
       0  840.14    19.6  834.71    39.2  830.19    48.9  828.79    88.1  825.47
    97.9  823.98   107.7  821.35   117.5  817.74   146.8  805.67   225.1  770.97
   254.5  758.48   274.1  750.51   283.9  746.88   293.6  743.77   313.2  738.58
     323   735.5   333.9  732.75   342.6  731.86   353.9  732.14   381.8  734.54
   469.8  738.82   479.6  739.92     509  745.34   518.8  746.75   528.6  747.85
   538.4  748.48   567.7  749.03   577.5  750.14   606.9  754.63   626.4  756.51
#Mann= 3 , 0 , 0
       0     .06       0   333.9    .045       0   353.9     .08       0
Bank Sta=333.9,353.9
XS Rating Curve= 0 ,0
Exp/Cntr=0.3,0.1

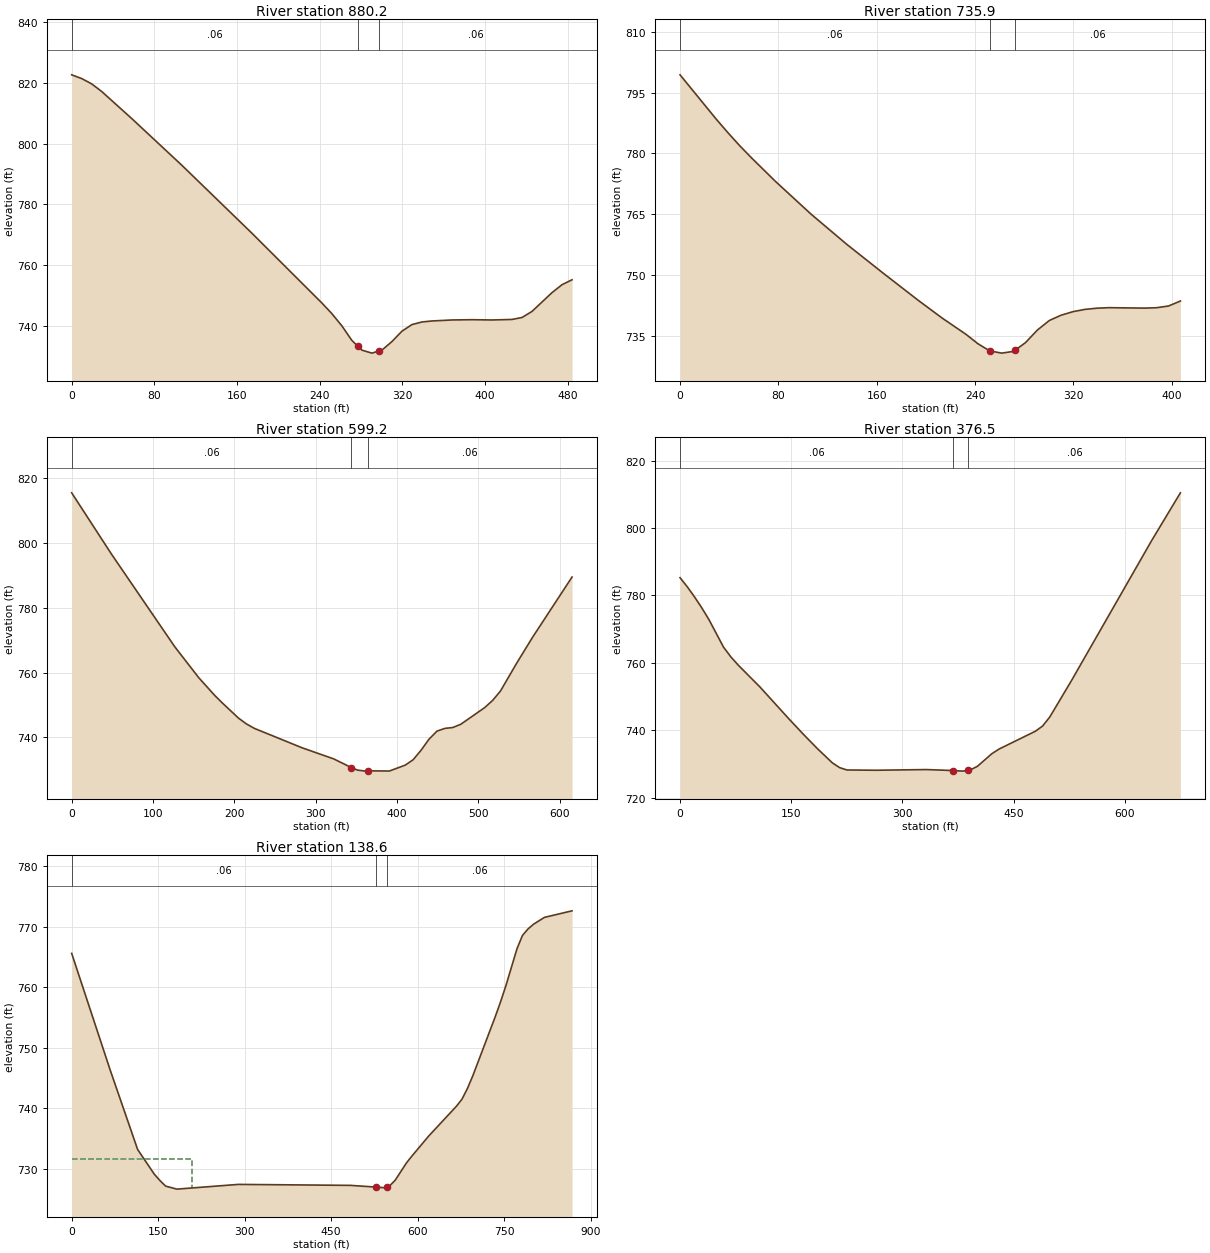
Type RM Length L Ch R = 1 ,880.2   ,144.1,144.3,144.5
XS GIS Cut Line= 2
     1898826.742      589364.685     1898624.382      589804.326
#Sta/Elev= 30
       0  822.67     9.7  821.44    19.4  819.68      29   817.2    58.1  808.28
   106.5  792.93   174.2   770.6     242   747.6   251.7  744.08   261.4  740.05
     271  735.29     277   733.3   280.7  732.08   290.4  731.09     297  731.76
   300.1  732.08   309.8   734.9   319.4  738.29   329.1  740.48   338.8  741.34
   348.5  741.67   367.8     742   387.2  742.09   406.5     742   425.9  742.17
   435.6  742.81   445.3  744.82   464.6  750.99   474.3   753.6     484  755.23
#Mann= 3 , 0 , 0
       0     .06       0     277    .045       0     297     .06       0
Bank Sta=277,297
XS Rating Curve= 0 ,0
Exp/Cntr=0.3,0.1

Type RM Length L Ch R = 1 ,735.9   ,136.2,136.7,137.3
XS GIS Cut Line= 2
      1898688.85      589325.288     1898515.143      589693.297
#Sta/Elev= 30
       0  799.39    29.1  788.58    38.8  785.17    48.4  781.95    58.1  778.92
    77.5  773.14   106.6  765.02   135.6  757.59   164.7   750.6   193.8  743.76
   213.2   739.4   232.5  735.41   242.2  733.09   251.9   731.3   252.5  731.27
   261.6  730.75   271.3  731.18   272.5  731.45     281  733.34   290.7  736.45
   300.4   738.8     310  740.11   319.7  740.98   329.4  741.54   339.1  741.83
   348.8  741.96   377.9  741.85   387.6  741.95   397.3  742.37     407   743.6
#Mann= 3 , 0 , 0
       0     .06       0   252.5    .045       0   272.5     .06       0
Bank Sta=252.5,272.5
XS Rating Curve= 0 ,0
Exp/Cntr=0.3,0.1

Type RM Length L Ch R = 1 ,599.2   ,222,222.7,223.4
XS GIS Cut Line= 2
     1898609.207       589203.58     1898331.876      589752.581
#Sta/Elev= 30
       0  815.53    48.8  796.65   126.9  767.94   156.2  758.45   175.7  753.01
   185.5  750.57     205  745.98   214.8  744.17   224.6  742.79   283.1  736.81
   322.2  733.36   343.8  730.69   351.5  729.89  361.36  729.59   363.8  729.69
   390.5  729.62     410  731.43   419.8  733.11   429.6  736.07   439.3  739.45
   449.1  741.95   458.9  742.79   468.6  743.06   478.4  744.07   507.7   749.2
   517.4   751.4   527.2  754.35   546.7  762.77   566.3  770.81   615.1  789.52
#Mann= 3 , 0 , 0
       0     .06       0   343.8    .045       0   363.8     .06       0
Bank Sta=343.8,363.8
XS Rating Curve= 0 ,0
Exp/Cntr=0.3,0.1

Type RM Length L Ch R = 1 ,376.5   ,234.6,237.2,240.4
XS GIS Cut Line= 2
      1898427.85      589094.364     1898108.071      589688.643
#Sta/Elev= 30
       0  785.27     9.8  782.56    19.6  779.55    29.3  776.34    39.1  772.79
    58.7  764.66    68.5   761.8    78.2  759.41   107.6  752.91   146.7  743.44
   166.3  738.85   185.8  734.47   205.4  730.38   215.2  728.96     225  728.26
   264.1  728.18   332.5  728.38   368.7  728.09   381.4  727.92   388.7  728.16
   391.2  728.24     401  729.34   420.6   733.1   430.3  734.47   479.2  739.74
     489   741.3   498.8  744.02   528.2  754.87   635.7  796.15   674.8  810.43
#Mann= 3 , 0 , 0
       0     .06       0   368.7    .045       0   388.7     .06       0
Bank Sta=368.7,388.7
XS Rating Curve= 0 ,0
Exp/Cntr=0.3,0.1

Type RM Length L Ch R = 1 ,138.6   ,127.8,138.2,148
XS GIS Cut Line= 4
      1898373.67      589018.166     1898259.535      589025.637
      1897979.49      589445.955      1897844.89      589654.684
#Sta/Elev= 30
       0  765.57    66.7  746.34   114.4   733.2   143.5   729.1   153.2  728.07
   162.9  727.16   182.4  726.66   289.2  727.44   483.5  727.28   527.1     727
   541.7   726.9   547.1  727.07   551.5  727.21   561.2  728.14   580.6  730.98
   590.3  732.14   619.4  735.44   667.2  740.33   676.8  741.48   686.3  743.25
   695.9  745.41   734.1  754.98   743.6   757.5   753.2  760.26   772.3  766.32
   781.8  768.52   791.4  769.59   800.9  770.37     820  771.51   867.8  772.59
#Mann= 3 , 0 , 0
       0     .06       0   527.1    .045       0   547.1     .06       0
#XS Ineff= 2 , 0
          208.42  731.71
Permanent Ineff=
       F       F
Bank Sta=527.1,547.1
XS Rating Curve= 0 ,0
Exp/Cntr=0.3,0.1

Chan Stop Cuts=-1
Use User Specified Reach Order=0
Composite Channel Slope=5